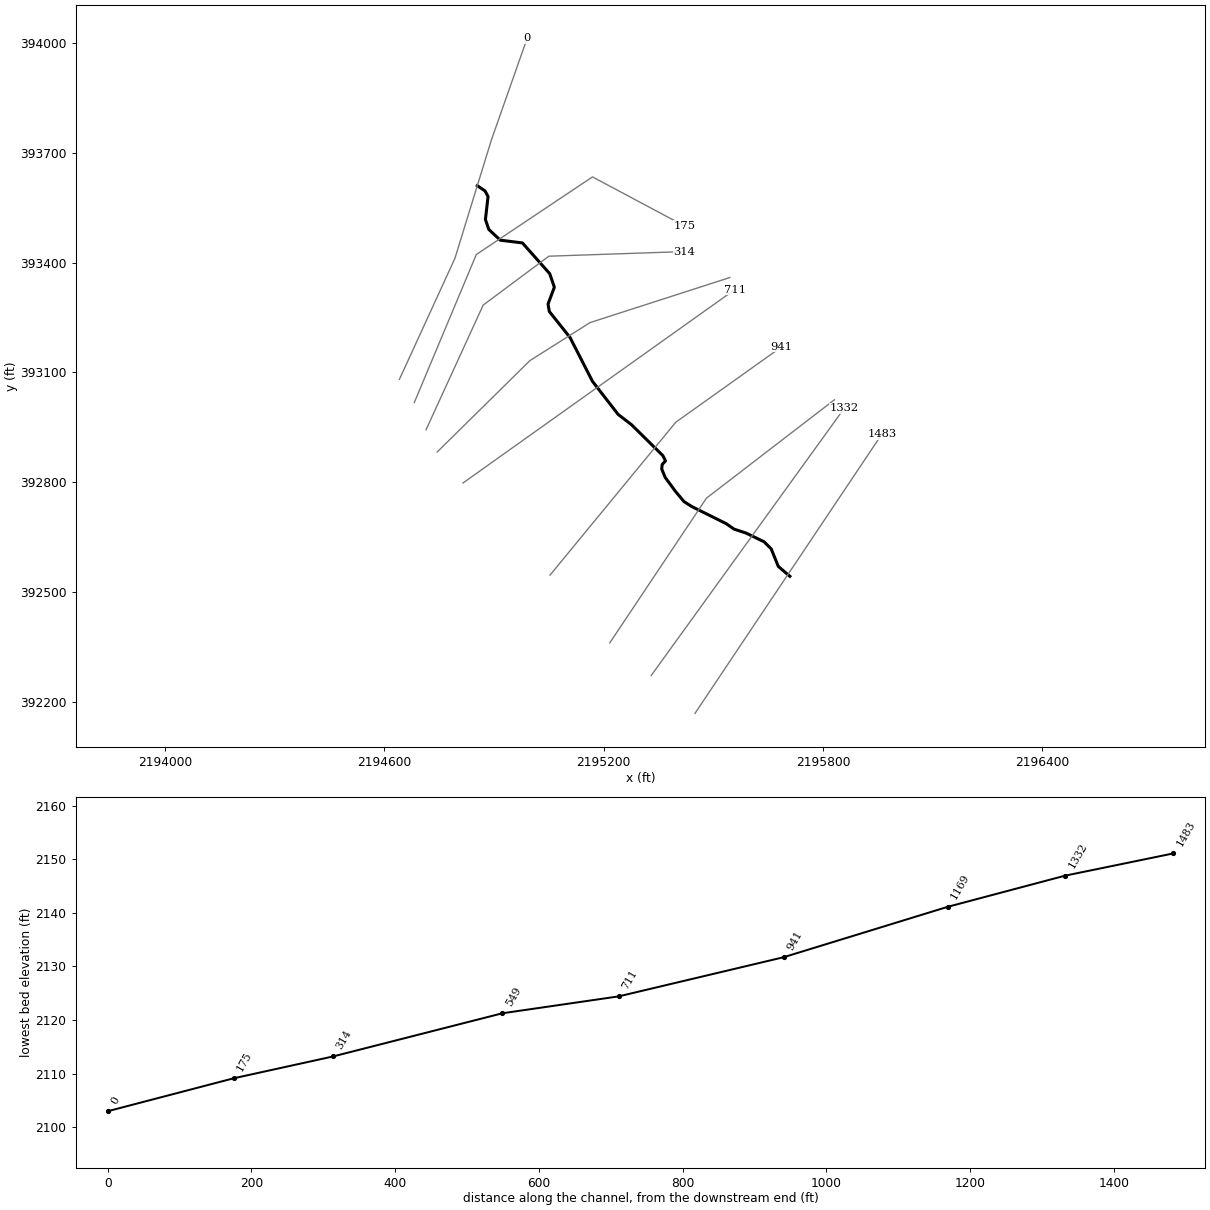
--- PERRYRN.prj (project) ---

Proj Title=PERRYRN
Current Plan=p01
Default Exp/Contr=0,0
English Units
Geom File=g01
Flow File=f01
Plan File=p01
Background Map Layer=Inundation Boundary (01pct Value_0)
BEGIN DESCRIPTION:
----------MODEL BY WOOD PLC 2021----------
Stream Name: Perry Run
Flood Zone: Enhanced Approximate
Pocahontas County, WV
HEC-RAS Version: RAS 6.1
Vertical Datum: NAVD88
Projection: NAD 1983 StatePlane West Virginia S FIPS 4702 (US Feet)
Terrain: 1-meter LIDAR (FEMA Region III 3DEP collected 2016-2018)
Land Use: 2019 NLCD
Hydrologic Method:
WV SIR2010-5033 regression equations
Model Notes:
Coincident peak tie-in with Oldham Run (OLDHMRN)
END DESCRIPTION:
DSS File=dss
DSS Export Rating Curves= 0
DSS Export Rating Curve Sorted= 0
DSS Export Volume Flow Curves= 0
DXF OffsetX= 0
DXF OffsetY= 0
DXF ScaleX= 0
DXF ScaleY= 0

--- PERRYRN.p01 (plan) ---

Plan Title=Floodplain
Program Version=6.10
Short Identifier=Floodplain
Geom File=g01
Flow File=f01
Subcritical Flow
K Sum by GR= 0
Std Step Tol= 0.01
Critical Tol= 0.01
Num of Std Step Trials= 20
Max Error Tol= 0.3
Flow Tol Ratio= 0.001
Split Flow NTrial= 30
Split Flow Tol= 0.02
Split Flow Ratio= 0.02
Log Output Level= 0
Friction Slope Method= 1
Unsteady Friction Slope Method= 2
Unsteady Bridges Friction Slope Method= 1
Parabolic Critical Depth
Global Vel Dist= 0 , 0 , 0
Global Log Level= 0
CheckData=True
Encroach Param=-1 ,0,0, 0
Computation Interval=0.1SEC
Output Interval=1SEC
Instantaneous Interval=Max Profile
Mapping Interval=1HOUR
Computation Time Step Use Courant=        0
Computation Time Step Use Time Series=    0
Computation Time Step Count To Double=0
Computation Time Step Max Doubling=0
Computation Time Step Max Halving=0
Computation Time Step Residence Courant=0
Run HTab= 0
Run UNet= 0
Run Sediment= 0
Run PostProcess= 0
Run WQNet= 0
Run RASMapper=-1
UNET Theta= 0
UNET Theta Warmup= 0
UNET ZTol= 0
UNET ZSATol= 0
UNET MxIter= 0
UNET Max Iter WO Improvement= 0
UNET MaxInSteps= 0
UNET DtIC= 0
UNET DtMin= 0
UNET MaxCRTS= 0
UNET WFStab= 0
UNET SFStab= 0
UNET WFX= 1
UNET SFX= 1
UNET Gravity=32.174
UNET 1D Methodology=Finite Difference
UNET DSS MLevel= 1
UNET Pardiso=0
UNET DZMax Abort= 0
UNET Use Existing IB Tables= 0
UNET Froude Reduction=False
UNET Froude Limit= 0
UNET Froude Power= 0
UNET D1 Cores= 0
UNET WindReference=Eulerian
UNET WindDragFormulation=Hsu (1988)
UNET D2 Coriolis=0
UNET D2 Cores= 0
UNET D2 Theta= 1
UNET D2 Theta Warmup= 1
UNET D2 Z Tol= 0.01
UNET D2 Volume Tol= 0.01
UNET D2 Max Iterations= 20
UNET D2 Equation= 0
UNET D2 RampUpFraction=0.1
UNET D2 TimeSlices= 1
UNET D2 Turbulence Formulation=Non-Conservative (original)
UNET D2 Eddy Viscosity=0.3
UNET D2 Transverse Eddy Viscosity=0.1
UNET D2 Smagorinsky Mixing=0
UNET D2 BCVolumeCheck=0
UNET D2 Cores=0
UNET D2 SolverType=PARDISO (Direct)
UNET D2 Minimum Iterations= 2147483647
UNET D2 Maximum Iterations= 2147483647
UNET D2 Restart Number= 10
UNET D2 Relaxation Coeff=1.3
UNET D2 SOR Precondition Iterations= 10
UNET D2 ILUT Maximum Fill= 8
UNET D2 ILUT Tolerance=1E-08
UNET D1D2 MaxIter= 0
UNET D1D2 ZTol=0.01
UNET D1D2 QTol=0.1
UNET D1D2 MinQTol=1
DSS File=dss
Write IC File= 0
Write IC File at Fixed DateTime=0
Write IC File at Sim End=0
Echo Input=False
Echo Parameters=False
Echo Output=False
Write Detailed= 0
HDF Write Warmup=0
HDF Write Time Slices=0
HDF Flush=0
HDF Compression= 1
HDF Chunk Size= 1
HDF Spatial Parts= 1
HDF Use Max Rows=0
HDF Fixed Rows= 1
Calibration Method= 0
Calibration Iterations= 20
Calibration Max Change=0.05
Calibration Tolerance=0.2
Calibration Maximum=1.5
Calibration Minimum=0.5
Calibration Optimization Method= 1
WQ AD Non Conservative
WQ ULTIMATE=-1
WQ Max Comp Step=1HOUR
WQ Output Interval=15MIN
WQ Output Selected Increments= 0
WQ Output face flow=0
WQ Output face velocity=0
WQ Output face area=0
WQ Output face dispersion=0
WQ Output cell volume=0
WQ Output cell surface area=0
WQ Output cell continuity=0
WQ Output cumulative cell continuity=0
WQ Output face conc=0
WQ Output face dconc_dx=0
WQ Output face courant=0
WQ Output face peclet=0
WQ Output face adv mass=0
WQ Output face disp mass=0
WQ Output cell mass=0
WQ Output cell source sink temp=0
WQ Output nsm pathways=0
WQ Output nsm derived pathways=0
WQ Create Restart=0
WQ Fixed Restart=0
WQ System Summary=0
WQ Write To DSS=0
Sorting and Armoring Iterations= 10
XS Update Threshold= 0.02
Bed Roughness Predictor= 0
Hydraulics Update Threshold= 0.02
Energy Slope Method= 1
Volume Change Method= 1
Sediment Retention Method= 0
Sediment TS Multiplier= 1
Warm Up Method= 0
XS Weighting Method= 0
Number of US Weighted Cross Sections= 1
Number of DS Weighted Cross Sections= 1
Upstream XS Weight=0
Main XS Weight=1
Downstream XS Weight=0
Number of DS XS's Weighted with US Boundary= 1
Upstream Boundary Weight= 1
Weight of XSs Associated with US Boundary= 0
Number of US XS's Weighted with DS Boundary= 1
Downstream Boundary Weight= 0.5
Weight of XSs Associated with DS Boundary= 0.5
Percentile Method= 0
Sediment Output Level= 3
Mass or Volume Output= 0
Output Increment Type= 1
Profile and TS Output Increment= 1
Transport Output Increment 1
XS Output Flag= 0
XS Output Increment= 10
Read HDF5 Sediment Hotstart= 0
Sediment Hotstart Type= 0
Write Gradation File= 0
Read Gradation Hotstart= 0
Write HDF5 File= 1
Write Binary Output= 1
Write DSS Sediment File= 0
DSS Sediment Output Type= 1
SV Curve= 0
Specific Gage Flag= 0
Subcell Erosion Methods= 0
Subcell Deposition Methods= 0
Advection Scheme= 1
Matrix Solver= 0
Implicit Weighting Factor= 1
Maximum Outer Loop Convergence Iterations= 5
Convergence Maximum Absolute= 0.001
Convergence RMSE= 0.0001
Grain Fractions Max Abs Error= 0.001
Max Subgrid Regions= 1
Max Subgrid Length Scale= 3.402823E+38
Initial Layer Thickness= 3.402823E+38
Min Layer Thickness= 3.402823E+38
Max Layer Thickness= 3.402823E+38
Number of Layers= 5

--- PERRYRN.f01 (steady flow) ---

Flow Title=Flow
Program Version=6.10
Number of Profiles= 6
Profile Names=01pct,10pct,04pct,02pct,0_2pct,01plus
River Rch & RM=PERRYRN,Main            ,1483
     524     276     367     443     733     775
River Rch & RM=PERRYRN,Main            ,0
    1160     628     825     985    1590    1710
Boundary for River Rch & Prof#=PERRYRN,Main            , 1
Up Type= 0
Dn Type= 1
Dn Known WS=2107.86
Boundary for River Rch & Prof#=PERRYRN,Main            , 2
Up Type= 0
Dn Type= 1
Dn Known WS=2106.74
Boundary for River Rch & Prof#=PERRYRN,Main            , 3
Up Type= 0
Dn Type= 1
Dn Known WS=2107.22
Boundary for River Rch & Prof#=PERRYRN,Main            , 4
Up Type= 0
Dn Type= 1
Dn Known WS=2107.5
Boundary for River Rch & Prof#=PERRYRN,Main            , 5
Up Type= 0
Dn Type= 1
Dn Known WS=2108.56
Boundary for River Rch & Prof#=PERRYRN,Main            , 6
Up Type= 0
Dn Type= 1
Dn Known WS=2108.86
DSS Import GetInterval= 0
DSS Import GetPeak= 0
DSS Import FillOption= 0

--- PERRYRN.g01 (geometry) ---

Geom Title=Geometry
Program Version=6.10

River Reach=PERRYRN         ,Main
Reach XY= 30
2195709.52332167392542.5599917442195677.83557628392569.601354549
2195658.43653706 392617.473177142195639.03749784 392636.87221636
2195589.28834887392660.9645715212195556.74802502392671.602754319
2195535.15877169392686.621365328     2195441.043      392733.402
     2195420.108      392746.739     2195396.393      392775.045
     2195368.388      392813.217     2195358.985      392836.083
2195360.38142166392848.5094837472195369.31300427392858.165248727
2195362.07118054392872.6488961952195276.37626635392957.136839762
     2195239.901      392985.2152195169.69054133393075.703266888
     2195108.252      393195.666     2195051.548      393266.848
     2195048.161       393287.13     2195065.385      393333.055
     2195052.801      393370.0582194978.14474399393454.217091517
       2194917.5       393461.78     2194886.095      393491.245
     2194876.896      393518.369      2194884.09      393581.082
     2194875.866        393596.4     2194854.713      393610.761

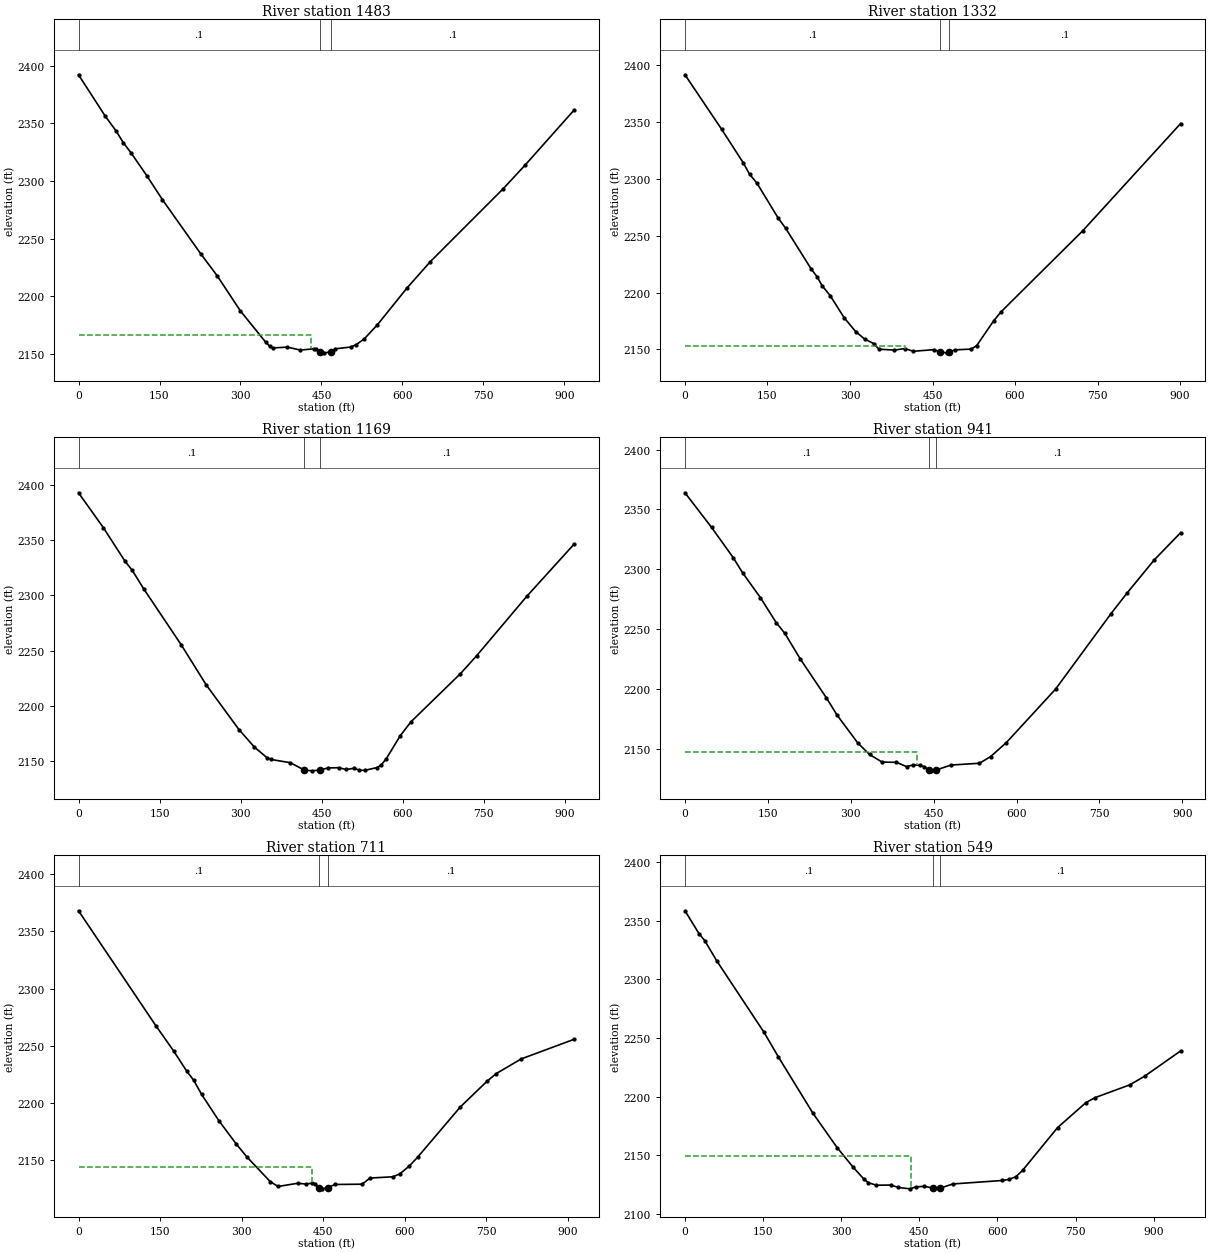
Type RM Length L Ch R = 1 ,1483    ,149.2,151,148.9
XS GIS Cut Line= 2
2195449.94377987392167.7170724352195960.55478091392930.594222797
#Sta/Elev= 30
       0    2392    49.9 2355.89      69 2343.72    83.1 2333.12    97.8 2324.02
   126.3  2304.7   155.5 2283.74   226.9 2236.55   256.9 2217.84   299.7  2187.5
   346.5 2160.42   354.4 2156.67   360.2 2155.32   386.8 2156.07   410.9 2153.47
   435.5 2154.58   439.8 2154.17   446.7 2152.03   455.4 2151.09   466.9 2151.84
   475.5 2154.57   504.4 2156.13   514.6 2158.29     529 2163.08   553.4  2175.3
   608.2 2207.16   651.2  2229.9   786.3 2293.14   826.9 2313.62     918  2361.5
#Mann= 3 ,-1,0
       0      .1       0   446.7    .045       0   466.9      .1       0
#XS Ineff= 2 , 0
          430.99 2166.38
Permanent Ineff=
       F       F
Bank Sta=446.7,466.9
XS Rating Curve= 0 ,0
Exp/Cntr(USF)=0,0
Exp/Cntr=0.3,0.1

Type RM Length L Ch R = 1 ,1332    ,160.9,163.2,164.4
XS GIS Cut Line= 2
2195330.25768996392271.2657532482195857.96551982393001.714308806
#Sta/Elev= 30
       0 2391.72    66.5 2343.84   105.9 2314.28   117.3 2304.22   130.7 2296.42
   168.9    2266   183.2 2256.44   229.1 2221.01   240.5 2213.66   249.1 2206.13
   263.9 2197.36   289.2 2177.95   310.6 2165.49   326.5 2159.14   342.9 2155.11
   352.7 2150.13   380.9 2149.35   399.4 2150.67   415.3 2148.33   452.5  2149.7
     464 2147.71   476.1 2146.93     480 2147.64   490.9 2149.54   520.5 2150.24
   530.4 2153.34   561.4 2175.24   574.8 2183.13   722.8 2254.21   901.1 2348.79
#Mann= 3 ,-1,0
       0      .1       0     464    .045       0     480      .1       0
#XS Ineff= 2 , 0
          399.36 2153.07
Permanent Ineff=
       F       F
Bank Sta=464,480
XS Rating Curve= 0 ,0
Exp/Cntr=0.3,0.1

Type RM Length L Ch R = 1 ,1169    ,226.9,228.2,224.6
XS GIS Cut Line= 3
2195217.08097088392360.6165556942195481.38952989392756.315496644
2195831.25461668393025.207441073
#Sta/Elev= 30
       0 2392.94    45.9 2361.39    86.3 2330.77    99.2 2322.86   120.9 2305.77
   190.1  2255.2   236.2 2219.04   296.8 2178.54   325.6 2162.53   348.7 2153.05
   356.6  2151.4     392 2148.47   417.9 2141.81   432.3 2141.12   446.8 2141.83
   461.2 2143.71   481.3 2143.96   495.6 2142.34   509.6 2143.41   519.7 2141.75
   529.8 2141.56   552.6 2144.12   560.1 2146.45   569.2 2151.89   595.4 2172.98
   615.1 2185.52   706.7 2229.12   736.7 2245.39   829.3  2299.1   917.1  2346.5
#Mann= 3 ,-1,0
       0      .1       0   417.9    .045       0   446.8      .1       0
Bank Sta=417.9,446.8
XS Rating Curve= 0 ,0
Exp/Cntr(USF)=0,0
Exp/Cntr=0.3,0.1

Type RM Length L Ch R = 1 ,941     ,232.8,229.7,226.4
XS GIS Cut Line= 3
2195053.53386937392545.7706916692195397.42335044392963.867902869
 2195687.0144924393170.201591514
#Sta/Elev= 30
       0 2363.87    48.2 2334.91    87.3  2309.7   104.9 2296.62   136.4 2276.41
     165 2255.51   180.5 2246.64   208.9 2224.93     256 2192.58   274.9 2178.49
   312.7 2154.99   333.9 2145.38   356.6 2139.04   382.5 2138.83   400.9  2135.3
   413.5 2136.66   424.9 2136.33   433.4 2135.23   441.9 2132.07   444.8 2131.72
   453.8 2132.33   481.7 2136.57   532.9 2138.06   552.9 2143.55   581.6 2155.35
   670.5  2199.9   770.8 2262.89   799.5  2279.9   849.2 2307.85   896.9 2330.56
#Mann= 3 ,-1,0
       0      .1       0   441.9    .045       0   453.8      .1       0
#XS Ineff= 2 , 0
          419.15 2147.82
Permanent Ineff=
       F       F
Bank Sta=441.9,453.8
XS Rating Curve= 0 ,0
Exp/Cntr(USF)=0,0
Exp/Cntr=0.3,0.1

Type RM Length L Ch R = 1 ,711     ,162.3,161.7,160.6
XS GIS Cut Line= 2
      2194815.63      392797.7432195558.85627365393326.651878631
#Sta/Elev= 30
       0 2368.14     143 2266.93     175 2245.33   199.1 2227.58   211.8 2219.71
   226.5 2207.24   258.1 2184.31   290.3 2163.72   309.8 2152.45   352.8 2130.77
   367.1 2126.48   403.2 2129.28     418 2128.63   430.4 2129.41     436 2128.82
   441.7 2125.33   447.4 2124.41458.31892125.393     472 2128.23     522 2128.49
   536.4 2133.87   578.5 2134.96   590.9 2137.39   608.1 2144.07   624.2  2152.2
   702.7 2196.19   751.8 2218.71   768.7 2225.41   814.6 2238.27   912.2 2255.51
#Mann= 3 ,-1,0
       0      .1       0   441.7    .045       0458.3189      .1       0
#XS Ineff= 2 , 0
          430.14 2143.37
Permanent Ineff=
       F       F
Bank Sta=441.7,458.3189
XS Rating Curve= 0 ,0
Exp/Cntr=0.3,0.1

Type RM Length L Ch R = 1 ,549     ,232.2,235.7,233.3
XS GIS Cut Line= 4
2194745.08563559392882.5720361342194998.47788481393132.344396072
2195163.18284679393236.4162127132195545.08116525393359.492448044
#Sta/Elev= 30
       0 2358.66    26.8 2339.26      38 2333.15    60.7 2316.13   151.9 2254.83
   179.4 2233.89   245.9  2185.7   292.5 2156.27   322.8 2139.83   343.4 2129.67
   351.9 2126.59   367.3 2124.36   395.7 2124.49   409.9 2122.43   432.2 2121.26
     443 2122.86   459.1 2123.41   476.5 2121.95   490.3 2121.91   514.6 2125.43
   609.2 2128.39   623.1 2129.42   635.7 2131.68   648.3 2137.01   715.6 2173.55
   770.2 2194.96   787.8 2199.18   854.3 2210.05   882.6 2217.38   951.9 2239.02
#Mann= 3 ,-1,0
       0      .1       0   476.5    .045       0   490.3      .1       0
#XS Ineff= 2 , 0
          433.18 2149.08
Permanent Ineff=
       F       F
Bank Sta=476.5,490.3
XS Rating Curve= 0 ,0
Exp/Cntr(USF)=0,0
Exp/Cntr=0.3,0.1

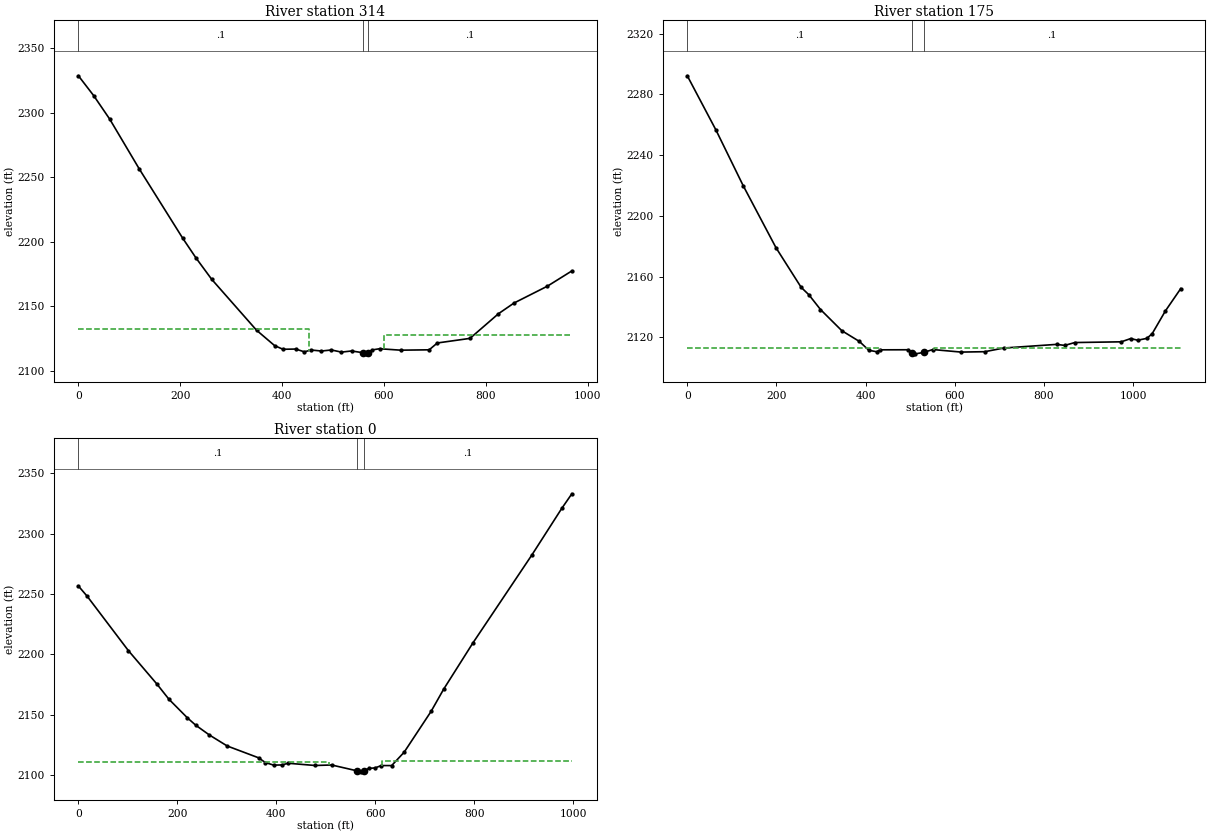
Type RM Length L Ch R = 1 ,314     ,137.7,138.4,136.8
XS GIS Cut Line= 4
2194714.47090733392943.1540920212194870.74063351393284.172241171
2195050.31619001393417.9070393662195420.18657349393430.590721618
#Sta/Elev= 30
       0  2328.7      30 2313.33    61.7 2294.98   119.3 2256.65   204.6 2202.96
     231 2187.47   261.8 2170.95   349.8 2131.52   385.4 2119.55   401.8 2116.74
   426.8 2116.91   443.8 2114.74   456.7 2116.17   477.3 2115.38   496.9  2116.2
   516.6 2114.54   536.5 2115.42558.26582114.104   565.5  2113.2569.19562113.892
   576.4  2116.2   591.4 2117.15   632.9 2116.04   688.9 2116.32   704.9 2121.62
     769 2125.18     825  2144.3   855.5 2152.58   921.1 2165.65   969.1 2177.46
#Mann= 3 ,-1,0
       0      .1       0558.2658    .045       0569.1956      .1       0
#XS Ineff= 2 , 0
          453.15 2132.63  601.01         2128.11
Permanent Ineff=
       F       F
Bank Sta=558.2658,569.1956
XS Rating Curve= 0 ,0
Exp/Cntr(USF)=0,0
Exp/Cntr=0.3,0.1

Type RM Length L Ch R = 1 ,175     ,175.2,175.2,175.2
XS GIS Cut Line= 4
 2194682.3526723393017.5684653792194851.93793271393422.434177162
2195169.71932158393634.7977014552195421.80551948393500.351729241
#Sta/Elev= 30
       0 2292.27    64.6 2256.38   125.3 2219.95   199.1 2178.96   255.4 2152.94
   272.8 2148.01   298.8 2138.32   346.6 2124.37   386.2 2117.26   407.2 2111.47
   424.6 2110.52   433.3 2111.76   495.9 2111.81   504.5 2109.87   511.4 2109.12
   530.6 2110.05   550.7 2111.95   614.1 2110.28   667.1 2110.53   710.3 2112.96
   828.5 2115.35   846.6 2114.67   869.3 2116.56   973.5 2117.04   994.6 2119.17
  1010.4  2118.1  1031.1 2119.32    1043 2122.48  1072.5 2137.39  1106.9  2152.1
#Mann= 3 ,-1,0
       0      .1       0   504.5    .045       0   530.6      .1       0
#XS Ineff= 2 , 0
          432.67 2112.73  553.02         2113.29
Permanent Ineff=
       F       F
Bank Sta=504.5,530.6
XS Rating Curve= 0 ,0
Exp/Cntr(USF)=0,0
Exp/Cntr=0.3,0.1

Type RM Length L Ch R = 1 ,0       ,0,0,0
XS GIS Cut Line= 4
2194641.63313591393080.9487009652194793.61554833393412.415105187
2194893.48970506393736.644251674 2194990.9805974 394013.70543159
#Sta/Elev= 30
       0 2256.61    17.9 2248.08   100.9 2203.27   158.7 2175.57   183.1 2162.97
   220.3 2147.64   237.4 2141.47   264.6  2133.5   300.8 2124.36   364.1 2114.61
     378 2110.64   394.7 2108.55   411.5 2108.67     424 2110.08   478.5 2108.23
   511.9 2108.65   563.6 2103.78   570.5 2102.98   577.2 2103.88   587.3 2105.84
   599.8 2106.23   612.4 2108.17   633.3 2108.16   658.5 2119.19     713 2152.96
   738.4 2171.31   797.4 2209.45   916.9 2282.36   977.1 2320.74   997.6 2332.87
#Mann= 3 ,-1,0
       0      .1       0   563.6    .045       0   577.2      .1       0
#XS Ineff= 2 , 0
          507.61 2111.46  613.65         2111.64
Permanent Ineff=
       F       F
Bank Sta=563.6,577.2
XS Rating Curve= 0 ,0
Exp/Cntr(USF)=0,0
Minor Loss Coefficient=0
Exp/Cntr=0.3,0.1
LCMann Table=0

Chan Stop Cuts=-1
Use User Specified Reach Order=0
Composite Channel Slope=5